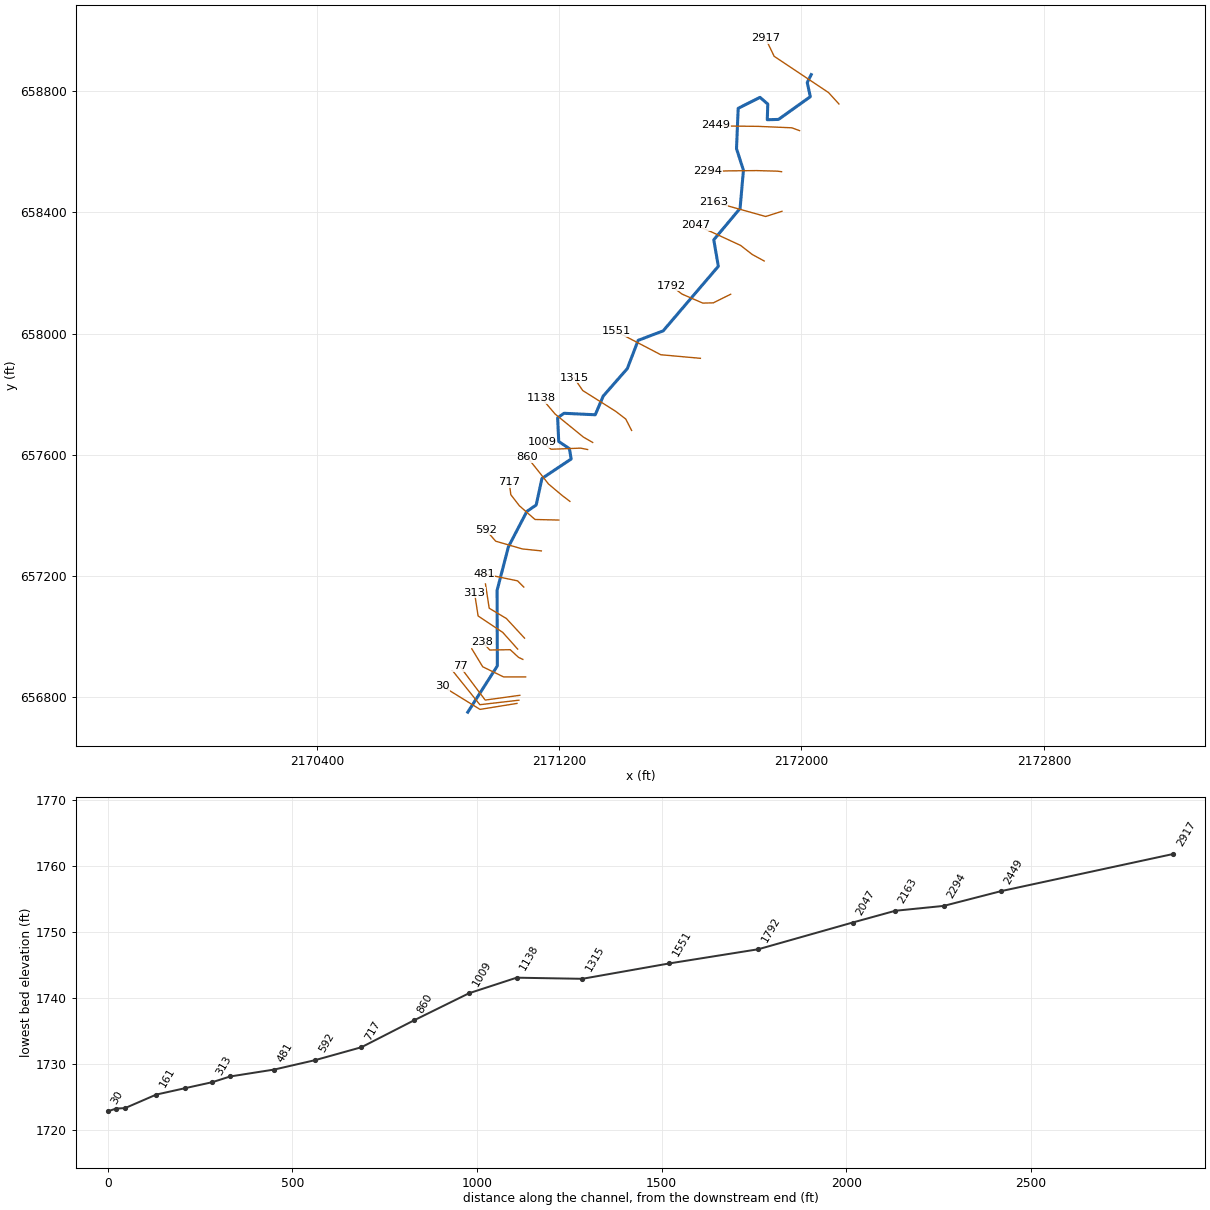
--- LIKANARVT1.prj (project) ---

Proj Title=LIKANARVT1
Current Plan=p01
Default Exp/Contr=0,0
English Units
Geom File=g01
Flow File=f01
Plan File=p01
BEGIN DESCRIPTION:
---------- MODELED AS PART OF WVEMD CTP PROGRAM, 2023----------
Stream Name: Little Kanawha River Tributary 1
Flood Zone:  AFH
Upshur County, WV
HEC-RAS Version: RAS 6.3
Vertical Datum: NAVD88
Projection: NAD 1983 StatePlane West Virginia S FIPS 4702 (US Feet)
Terrain: 1-meter LIDAR (FEMA Region III 3DEP collected 2016-2018)
Land Use: 2019 NLCD
Hydrologic Method:
WV SIR2010-5033 regression equations
Additional Model Notes:
None
END DESCRIPTION:
DSS Export Rating Curves= 0
DSS Export Rating Curve Sorted= 0
DSS Export Volume Flow Curves= 0
DXF OffsetX= 0
DXF OffsetY= 0
DXF ScaleX= 0
DXF ScaleY= 0

--- LIKANARVT1.p01 (plan) ---

Plan Title=Floodplain
Program Version=6.30
Short Identifier=Floodplain
Geom File=g01
Flow File=f01
Subcritical Flow
K Sum by GR= 0
Std Step Tol= 0.01
Critical Tol= 0.01
Num of Std Step Trials= 20
Max Error Tol= 0.3
Flow Tol Ratio= 0.001
Split Flow NTrial= 30
Split Flow Tol= 0.02
Split Flow Ratio= 0.02
Log Output Level= 0
Friction Slope Method= 1
Unsteady Friction Slope Method= 2
Unsteady Bridges Friction Slope Method= 1
Parabolic Critical Depth
Global Vel Dist= 0 , 0 , 0
Global Log Level= 0
CheckData=False
Encroach Param=-1 ,0,0, 0
Mapping Interval=1HOUR
Computation Time Step Use Courant=        0
Computation Time Step Use Time Series=    0
Computation Time Step Count To Double=0
Computation Time Step Max Doubling=0
Computation Time Step Max Halving=0
Computation Time Step Residence Courant=0
Run HTab= 0
Run UNet= 0
Run Sediment= 0
Run PostProcess= 0
Run WQNet= 0
Run RASMapper=-1
UNET Theta= 0
UNET Theta Warmup= 0
UNET ZTol= 0
UNET ZSATol= 0
UNET MxIter= 0
UNET Max Iter WO Improvement= 0
UNET MaxInSteps= 0
UNET DtIC= 0
UNET DtMin= 0
UNET MaxCRTS= 0
UNET WFStab= 0
UNET SFStab= 0
UNET WFX= 1
UNET SFX= 1
UNET Gravity=32.17405
UNET 1D Methodology=Finite Difference
UNET DSS MLevel= 1
UNET Pardiso=0
UNET DZMax Abort= 0
UNET Use Existing IB Tables= 0
UNET Froude Reduction=False
UNET Froude Limit= 0
UNET Froude Power= 0
UNET D1 Cores= 0
UNET WindReference=Eulerian
UNET WindDragFormulation=Hsu (1988)
UNET D2 Coriolis=0
UNET D2 Cores= 0
UNET D2 Theta= 1
UNET D2 Theta Warmup= 1
UNET D2 Z Tol= 0.01
UNET D2 Volume Tol= 0.01
UNET D2 Max Iterations= 20
UNET D2 Equation= 0
UNET D2 RampUpFraction=0.1
UNET D2 TimeSlices= 1
UNET D2 Turbulence Formulation=Non-Conservative (original)
UNET D2 Eddy Viscosity=0.3
UNET D2 Transverse Eddy Viscosity=0.1
UNET D2 Smagorinsky Mixing=0
UNET D2 BCVolumeCheck=0
UNET D2 Cores=0
UNET D2 SolverType=PARDISO (Direct)
UNET D2 Minimum Iterations= 3
UNET D2 Maximum Iterations= 30
UNET D2 Restart Number= 10
UNET D2 Relaxation Coeff=1.3
UNET D2 SOR Precondition Iterations= 10
UNET D2 ILUT Maximum Fill= 8
UNET D2 ILUT Tolerance=1E-08
UNET D2 Convergence Tolerance=0.00001
UNET D1D2 MaxIter= 0
UNET D1D2 ZTol=0.01
UNET D1D2 QTol=0.1
UNET D1D2 MinQTol=1
Write IC File= 0
Write IC File at Fixed DateTime=0
Write IC File at Sim End=0
Echo Input=False
Echo Parameters=False
Echo Output=False
Write Detailed= 0
HDF Write Warmup=0
HDF Write Time Slices=0
HDF Flush=0
HDF Compression= 1
HDF Chunk Size= 1
HDF Spatial Parts= 1
HDF Use Max Rows=0
HDF Fixed Rows= 1
Calibration Method= 0
Calibration Iterations= 20
Calibration Max Change=0.05
Calibration Tolerance=0.2
Calibration Maximum=1.5
Calibration Minimum=0.5
Calibration Optimization Method= 1
WQ AD Non Conservative
WQ ULTIMATE=-1
WQ Max Comp Step=1HOUR
WQ Output Interval=15MIN
WQ Output Selected Increments= 0
WQ Output face flow=0
WQ Output face velocity=0
WQ Output face area=0
WQ Output face dispersion=0
WQ Output cell volume=0
WQ Output cell surface area=0
WQ Output cell continuity=0
WQ Output cumulative cell continuity=0
WQ Output face conc=0
WQ Output face dconc_dx=0
WQ Output face courant=0
WQ Output face peclet=0
WQ Output face adv mass=0
WQ Output face disp mass=0
WQ Output cell mass=0
WQ Output cell source sink temp=0
WQ Output nsm pathways=0
WQ Output nsm derived pathways=0
WQ Create Restart=0
WQ Fixed Restart=0
WQ System Summary=0
WQ Write To DSS=0
Sorting and Armoring Iterations= 10
XS Update Threshold= 0.02
Bed Roughness Predictor= 0
Hydraulics Update Threshold= 0.02
Energy Slope Method= 1
Volume Change Method= 1
Sediment Retention Method= 0
Sediment TS Multiplier= 1
Warm Up Method= 0
XS Weighting Method= 0
Number of US Weighted Cross Sections= 1
Number of DS Weighted Cross Sections= 1
Upstream XS Weight=0
Main XS Weight=1
Downstream XS Weight=0
Number of DS XS's Weighted with US Boundary= 1
Upstream Boundary Weight= 1
Weight of XSs Associated with US Boundary= 0
Number of US XS's Weighted with DS Boundary= 1
Downstream Boundary Weight= 0.5
Weight of XSs Associated with DS Boundary= 0.5
Percentile Method= 0
Sediment Output Level= 3
Mass or Volume Output= 0
Output Increment Type= 1
Profile and TS Output Increment= 1
Transport Output Increment 1
XS Output Flag= 0
XS Output Increment= 10
Read HDF5 Sediment Hotstart= 0
Sediment Hotstart Type= 0
Write Gradation File= 0
Read Gradation Hotstart= 0
Write HDF5 File= 1
Write Binary Output= 1
Write DSS Sediment File= 0
DSS Sediment Output Type= 1
SV Curve= 0
Specific Gage Flag= 0
Subcell Erosion Methods= 0
Subcell Deposition Methods= 0
Advection Scheme= 1
Matrix Solver= 0
Implicit Weighting Factor= 1
Maximum Outer Loop Convergence Iterations= 5
Convergence Maximum Absolute= 0.001
Convergence RMSE= 0.0001
Grain Fractions Max Abs Error= 0.001
Max Subgrid Regions= 1
Max Subgrid Length Scale= 3.402823E+38
Initial Layer Thickness= 3.402823E+38
Min Layer Thickness= 3.402823E+38
Max Layer Thickness= 3.402823E+38
Number of Layers= 5

--- LIKANARVT1.f01 (steady flow) ---

Flow Title=Flows
Program Version=6.30
Number of Profiles= 1
Profile Names=01pct
River Rch & RM=LIKANARVT1,Main,2917
     667
Boundary for River Rch & Prof#=LIKANARVT1,Main            , 1
Up Type= 0
Dn Type= 3
Dn Slope=0.015
DSS Import GetInterval= 0
DSS Import GetPeak= 0
DSS Import FillOption= 0

--- LIKANARVT1.g01 (geometry) ---

Geom Title=Geometry
Program Version=6.30

River Reach=LIKANARVT1      ,Main
Reach XY= 30
      2172032.11      658854.494     2172018.918      658828.338
     2172029.134      658781.665     2171924.226      658706.747
     2171887.053      658705.631     2171888.713      658757.255
     2171863.187      658779.462     2171791.017      658743.376
     2171785.465      658610.167     2171808.358      658539.198
     2171797.284      658413.343     2171710.462      658309.466
     2171725.428      658222.157     2171543.371      658009.194
     2171460.755      657977.859     2171424.956      657884.684
     2171345.488      657794.056      2171319.19      657732.359
     2171215.913       657737.31     2171194.937        657722.2
     2171198.629      657644.192     2171233.827      657620.698
     2171239.636      657586.502     2171143.085      657522.029
     2171124.255       657434.72     2171093.464      657413.601
     2171032.482      657296.675     2170995.166      657153.164
     2170995.968      656903.886     2170898.357      656751.246

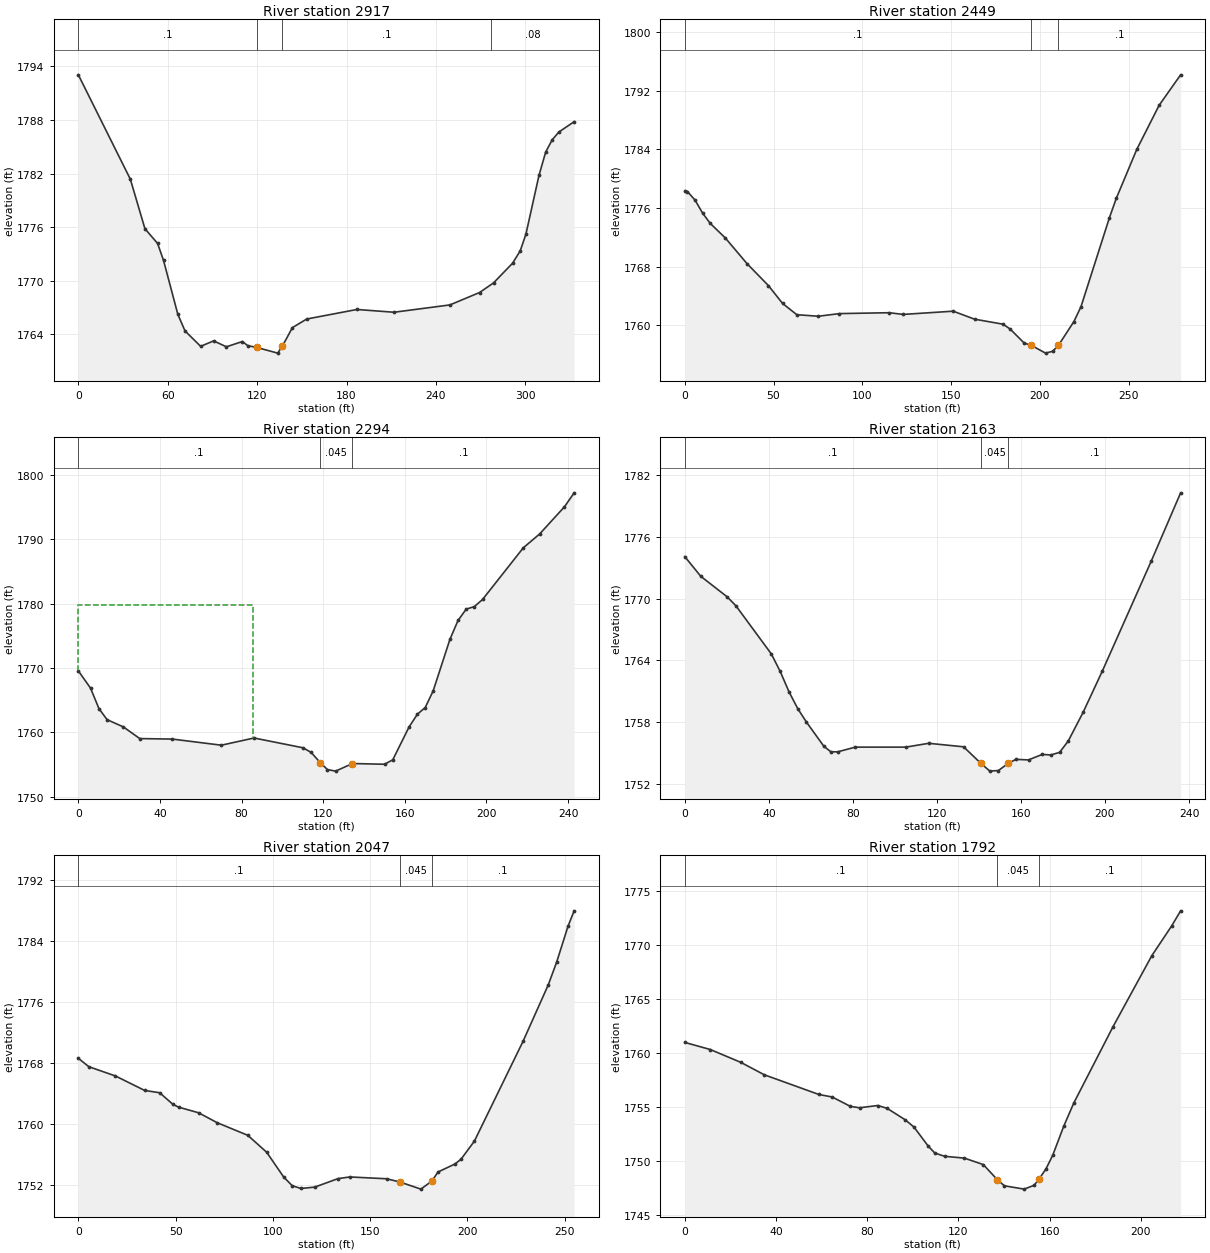
Type RM Length L Ch R = 1 ,2917    ,467.8,467.8,467.8
XS GIS Cut Line= 4
2172123.69907338658757.5796008842172089.20852647658795.354143034
2171909.76655598658914.9018861282171881.15625187658974.357674366
#Sta/Elev= 30
       0 1793.06    34.9 1781.37    44.7 1775.82    53.2 1774.17    57.2 1772.26
    66.8 1766.22    71.6 1764.37    82.1 1762.64    90.8 1763.25    99.4 1762.59
   110.1 1763.18   113.8 1762.71   119.7 1762.52   133.8 1761.88   136.9 1762.65
   143.7 1764.74   153.3  1765.7     187 1766.77   211.9 1766.46   249.4 1767.28
   269.3 1768.67   278.7 1769.75   291.5 1771.96   296.6 1773.34   300.4 1775.19
   309.2  1781.8   313.7 1784.41   318.1 1785.79   322.6 1786.66   332.8 1787.81
#Mann= 4, -1 ,  0
       0     0.1       0   119.7   0.045       0   136.9     0.1       0
  276.77    0.08       0
Bank Sta=119.7,136.9
XS Rating Curve= 0 ,0
Exp/Cntr(USF)=0,0
Exp/Cntr=0.3,0.1

Type RM Length L Ch R = 1 ,2449    ,154.5,154.5,155.8
XS GIS Cut Line= 5
2171993.57869094658669.6846592592171967.78754372 658679.06563582
2171856.93606502658683.7675450062171758.54577076658684.842039002
2171716.06000215658686.954335693
#Sta/Elev= 30
       0 1778.35     1.5 1778.25     5.8 1777.08      10 1775.32    14.3 1773.92
    22.8 1771.93    35.1 1768.41    47.1 1765.43    55.1 1762.99    63.1 1761.46
    75.2 1761.25    87.1 1761.61   115.1 1761.73   123.1  1761.5   151.2 1761.94
   163.2 1760.85   179.2 1760.17   183.2 1759.52   191.2 1757.59   195.2 1757.28
   203.2 1756.22   207.2 1756.47   210.5 1757.29   219.2 1760.53   223.2 1762.57
   239.2 1774.69   243.1 1777.35   254.6    1784   267.2 1790.02   279.3 1794.17
#Mann= 3, -1 ,  0
       0     0.1       0   195.2   0.045       0   210.5     0.1       0
Bank Sta=195.2,210.5
XS Rating Curve= 0 ,0
Exp/Cntr(USF)=0,0
Exp/Cntr=0.3,0.1

Type RM Length L Ch R = 1 ,2294    ,133,131.2,127.3
XS GIS Cut Line= 5
2171934.16797721 658534.280571932171919.28862633658536.057295027
2171851.67162161658537.8847816412171758.92667594658536.971038334
2171691.30967122 658535.14355172
#Sta/Elev= 30
       0 1769.58       6 1766.88    10.1 1763.71    14.1 1761.99    22.1 1760.86
    30.1 1759.05    46.1 1758.97    70.1 1758.02    86.1 1759.14   110.1 1757.62
   114.1  1756.9   118.5 1755.33   122.1 1754.23   126.1 1753.99   134.3 1755.17
   150.1 1755.06   154.1 1755.75   162.1 1760.86   166.2 1762.85     170 1763.87
   173.9 1766.46   182.1 1774.46   186.1 1777.42   190.1 1779.17   194.1 1779.57
   198.1 1780.67   218.1 1788.71   226.1 1790.86   238.2 1795.06     243 1797.25
#Mann= 3, -1 ,  0
       0     0.1       0   118.5   0.045       0   134.3     0.1       0
#XS Ineff= 2 , 0
           85.77 1779.77
Permanent Ineff=
       F       F
Bank Sta=118.5,134.3
XS Rating Curve= 0 ,0
Exp/Cntr(USF)=0,0
Exp/Cntr=0.3,0.1

Type RM Length L Ch R = 1 ,2163    ,114.5,115.8,111.9
XS GIS Cut Line= 3
2171935.39145111 658403.51308572 2171881.8286483658386.456183438
2171708.72193224 658434.86719057
#Sta/Elev= 30
       0 1774.07     7.6 1772.16    20.2 1770.16    24.4 1769.28    41.2 1764.62
    45.4 1762.93    49.6 1760.95    53.8  1759.3    57.9 1758.01    66.2 1755.66
    69.5 1755.13    72.7 1755.12    81.2 1755.58   105.2 1755.58   116.1 1755.95
   132.7 1755.61   140.9 1754.01   145.2 1753.25   149.3 1753.31   153.9    1754
   157.6 1754.39   163.6 1754.34   170.1 1754.87   174.2 1754.82   178.4 1755.07
   182.5 1756.17   189.6 1758.96   198.8 1762.99   222.1 1773.67     236 1780.26
#Mann= 3, -1 ,  0
       0     0.1       0   140.9   0.045       0   153.9     0.1       0
Bank Sta=140.9,153.9
XS Rating Curve= 0 ,0
Exp/Cntr(USF)=0,0
Exp/Cntr=0.3,0.1

Type RM Length L Ch R = 1 ,2047    ,255.1,255.2,250
XS GIS Cut Line= 5
2171876.93750095658239.6842512932171837.45476546658261.117736273
2171799.10010813658291.011807429 2171700.3932694658336.698972782
2171651.88590866658357.004379605
#Sta/Elev= 30
       0 1768.64     5.4 1767.54    19.1 1766.32    34.1 1764.42    41.8 1764.12
    48.7 1762.58    51.5 1762.23    61.8 1761.49    71.5 1760.17    87.1 1758.53
    96.8 1756.31   105.6 1753.04     110  1751.9   114.4 1751.55   121.5 1751.72
   133.5 1752.84   139.6 1753.06   158.5 1752.82   165.4 1752.39   176.1 1751.46
   181.8 1752.53   184.9 1753.71   193.7 1754.77   196.8 1755.41   203.6 1757.76
   228.6 1770.86   241.6 1778.29   245.9 1781.27   251.8 1786.03   254.9 1788.01
#Mann= 3, -1 ,  0
       0     0.1       0   165.4   0.045       0   181.8     0.1       0
Bank Sta=165.4,181.8
XS Rating Curve= 0 ,0
Exp/Cntr(USF)=0,0
Exp/Cntr=0.3,0.1

Type RM Length L Ch R = 1 ,1792    ,240,240.7,236.5
XS GIS Cut Line= 5
2171766.16416848658129.9891956832171709.00952463658101.617465999
2171674.05884313658100.7950970232171604.97984912 658130.81156466
 2171570.8515366658157.538556391
#Sta/Elev= 30
       0 1760.99    11.2 1760.33    24.5 1759.15    34.9 1757.99    58.8 1756.17
    64.6 1755.94    72.6 1755.07    76.6 1754.94    84.6 1755.15    88.7 1754.89
    96.7 1753.82   100.5 1753.15   106.6 1751.43   109.6 1750.75   113.9 1750.45
   122.6 1750.28   130.9 1749.68     137 1748.29   140.1 1747.72   148.8 1747.41
   153.2 1747.77   155.2 1748.31   158.3 1749.26   161.3 1750.53   166.2 1753.26
   170.6  1755.4   187.7 1762.42   204.8 1769.03   213.4 1771.75   217.4 1773.17
#Mann= 3, -1 ,  0
       0     0.1       0     137   0.045       0   155.2     0.1       0
Bank Sta=137,155.2
XS Rating Curve= 0 ,0
Exp/Cntr(USF)=0,0
Exp/Cntr=0.3,0.1

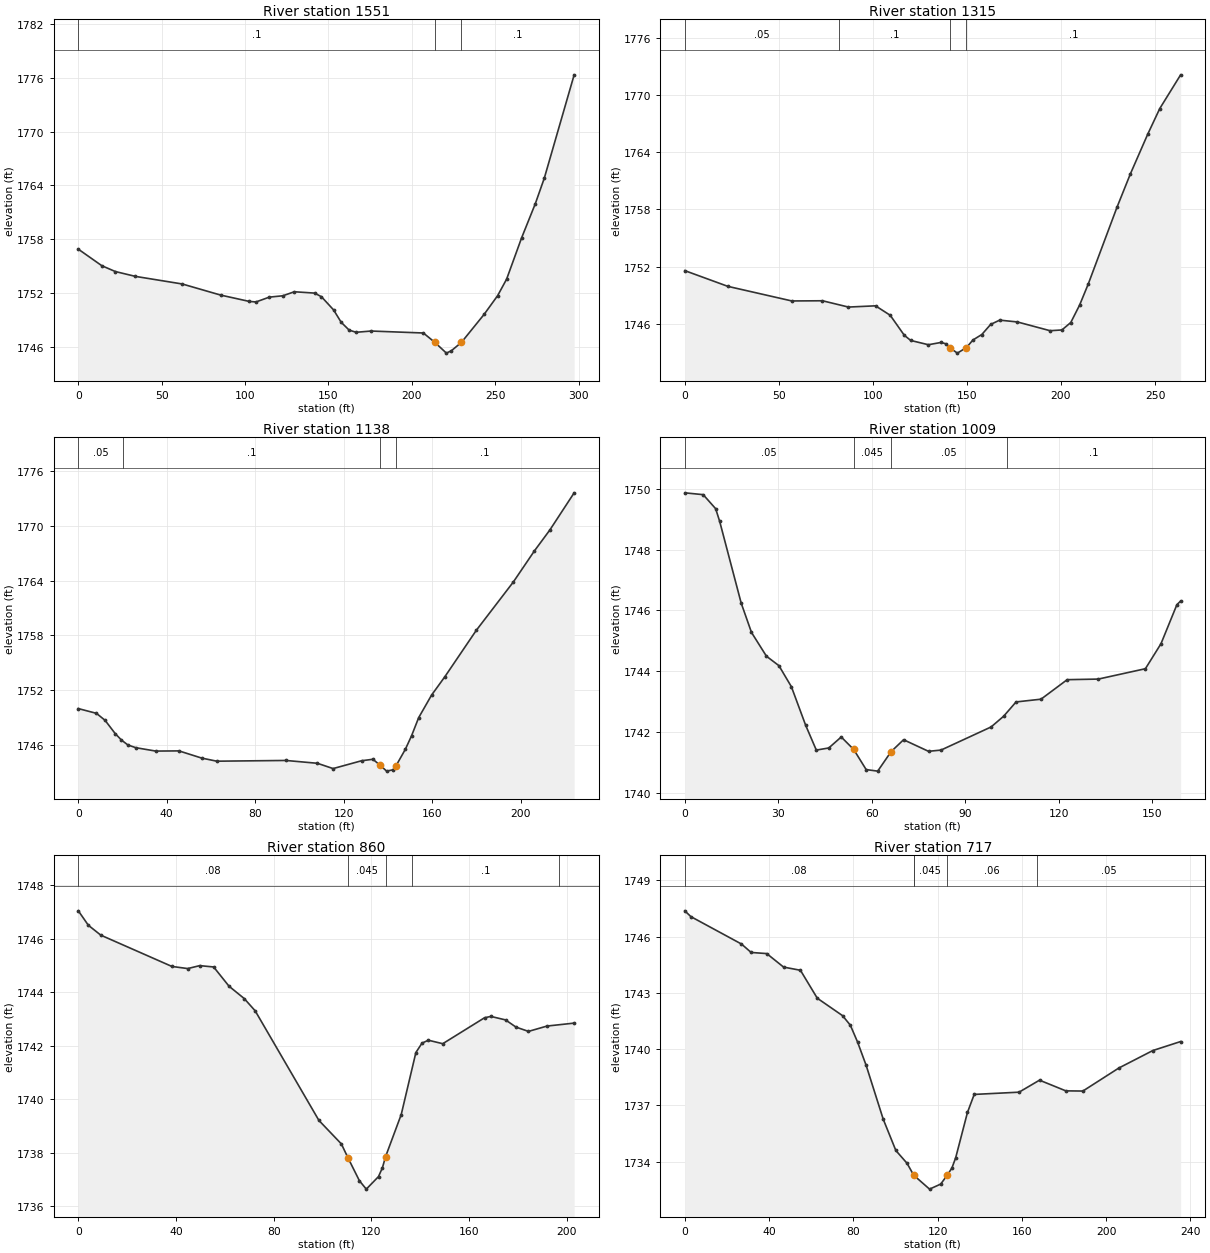
Type RM Length L Ch R = 1 ,1551    ,237.1,236.1,235.3
XS GIS Cut Line= 3
2171666.23861195657918.6351054692171535.58959186657930.448450296
2171388.21418333658007.207091296
#Sta/Elev= 30
       0 1756.88    14.1 1755.03    22.2 1754.38    34.2 1753.84    62.3 1752.99
    85.3 1751.75   102.5 1751.04   106.5 1750.98   114.5 1751.52   122.6 1751.67
   129.5 1752.12   141.7 1751.97   145.8 1751.56   153.1 1750.08   157.6 1748.71
   162.4 1747.83   166.6 1747.59   175.6 1747.73   206.9 1747.51   213.81746.457
   220.7 1745.26   223.7 1745.53   229.7 1746.46   243.3 1749.59   251.4 1751.68
   256.8 1753.53   265.8 1758.15     274 1761.96   279.4 1764.82   297.3 1776.37
#Mann= 3, -1 ,  0
       0     0.1       0   213.8   0.045       0   229.7     0.1       0
Bank Sta=213.8,229.7
XS Rating Curve= 0 ,0
Exp/Cntr(USF)=0,0
Exp/Cntr=0.3,0.1

Type RM Length L Ch R = 1 ,1315    ,178.9,177.9,175.9
XS GIS Cut Line= 5
2171439.13374677657680.7547498332171419.94513732657718.218225422
2171386.59350662657743.8030380192171277.85805308657812.333786047
2171249.07513891657854.365978171
#Sta/Elev= 30
       0 1751.57    22.9 1749.92    56.9 1748.39    73.2 1748.41      87 1747.75
   101.4 1747.88   109.2 1746.89   116.7 1744.79   120.1 1744.25   129.5  1743.8
   136.2 1744.04     139 1743.89  140.82  1743.5   144.9 1742.92  149.71  1743.5
   153.2  1744.3   157.9 1744.87   162.6 1745.93   167.4 1746.38   176.8 1746.19
   194.2 1745.27   200.5 1745.35   205.2 1746.13   209.9 1747.96   214.5 1750.17
   229.8 1758.23   236.9 1761.72   246.1 1765.87   252.5 1768.56   263.6  1772.1
#Mann= 4, -1 ,  0
       0    0.05       0   82.09     0.1       0  140.82   0.045       0
  149.71     0.1       0
Bank Sta=140.82,149.71
XS Rating Curve= 0 ,0
Exp/Cntr(USF)=0,0
Exp/Cntr=0.3,0.1

Type RM Length L Ch R = 1 ,1138    ,122.5,128.9,130.3
XS GIS Cut Line= 4
2171310.70255486657641.1142073512171280.35713963  657658.5073112
2171186.73043168657734.7409153072171142.32250695657786.920226856
#Sta/Elev= 30
       0 1749.95     8.2 1749.43    12.1 1748.66    16.7  1747.2    19.5  1746.5
    22.4 1745.96      26 1745.66      35 1745.29    45.5 1745.31    55.8 1744.52
    62.6 1744.18    93.9 1744.26   108.1 1743.95   115.2 1743.37   128.1 1744.23
   133.2 1744.39   136.5 1743.73   139.4 1743.09   142.2 1743.23   143.5 1743.61
   147.9  1745.5   150.7 1746.98   153.9 1748.96   159.7 1751.42   165.8 1753.47
   179.9 1758.52   196.7 1763.84   206.2 1767.24   213.2 1769.54   224.2 1773.62
#Mann= 4, -1 ,  0
       0    0.05       0      20     0.1       0   136.5   0.045       0
   143.5     0.1       0
Bank Sta=136.5,143.5
XS Rating Curve= 0 ,0
Exp/Cntr(USF)=0,0
Exp/Cntr=0.3,0.1

Type RM Length L Ch R = 1 ,1009    ,155.8,148.5,141.8
XS GIS Cut Line= 4
2171293.92165902657617.7589284232171271.07807635657622.327644958
2171173.76441415 657618.672671732171143.15401336657641.973126059
#Sta/Elev= 30
       0 1749.86     5.9  1749.8     9.9 1749.34    11.2 1748.92    18.1 1746.24
    21.4 1745.28    26.2  1744.5    30.2 1744.19    34.2  1743.5    38.8 1742.23
    42.2 1741.42    46.2 1741.49    50.2 1741.85    54.2 1741.44    58.2 1740.78
    61.9 1740.73    66.2 1741.37    70.2 1741.76    78.2 1741.38    82.2 1741.42
    98.3 1742.18   102.3 1742.53   106.3    1743   114.3 1743.09   122.7 1743.73
   132.7 1743.75   147.8 1744.09   152.8 1744.91   157.9 1746.19   159.1 1746.31
#Mann= 4, -1 ,  0
       0    0.05       0    54.2   0.045       0    66.2    0.05       0
   103.3     0.1       0
Bank Sta=54.2,66.2
XS Rating Curve= 0 ,0
Exp/Cntr(USF)=0,0
Exp/Cntr=0.3,0.1

Type RM Length L Ch R = 1 ,860     ,139.6,143.1,142
XS GIS Cut Line= 5
2171235.47303084 657446.720010052171209.19834204657466.703576175
2171164.79041732 657504.080246152171136.66539833657539.976651967
2171095.21800192657591.785897477
#Sta/Elev= 30
       0 1747.04     4.1  1746.5     9.2 1746.13    38.3 1744.96    44.8 1744.88
    49.7 1744.99    55.4 1744.94    61.7 1744.22    67.9 1743.76    72.4  1743.3
    98.5  1739.2   107.7 1738.32  110.35 1737.81   115.1 1736.94   117.9 1736.63
   122.9  1737.1   124.5 1737.43  125.81 1737.85   132.2 1739.42   138.2 1741.74
   140.7 1742.09   143.3  1742.2   149.2 1742.07   166.3 1743.04   168.9 1743.09
   174.9 1742.96   179.2 1742.69   184.3 1742.53   191.9 1742.73     203 1742.84
#Mann= 5, -1 ,  0
       0    0.08       0  110.35   0.045       0  125.81    0.08       0
  136.66     0.1       0  196.66    0.08       0
Bank Sta=110.35,125.81
XS Rating Curve= 0 ,0
Exp/Cntr(USF)=0,0
Exp/Cntr=0.3,0.1

Type RM Length L Ch R = 1 ,717     ,119.7,124.7,129.5
XS GIS Cut Line= 5
2171199.01799581 657385.101526422171120.43607141657386.929013034
2171068.80957456657432.1593067322171040.48353204657468.709039014
 2171035.0010722657510.284359485
#Sta/Elev= 30
       0 1747.37     2.9 1747.06    26.9  1745.6    31.5 1745.15    38.9 1745.09
    46.9 1744.37    54.9  1744.2    62.9 1742.71    74.9 1741.78    78.6 1741.27
      82 1740.38    86.1 1739.13    94.2 1736.26   100.2 1734.59   105.5 1733.91
   108.7 1733.27   116.2 1732.53   121.5  1732.8   124.5 1733.26   126.8 1733.65
   128.6  1734.2   134.2 1736.62   137.4 1737.58   158.7  1737.7   168.4 1738.34
   180.9 1737.77     189 1737.76   206.1 1738.99   222.2 1739.92   235.4  1740.4
#Mann= 5, -1 ,  0
       0    0.08       0   108.6    0.06       0   108.7   0.045       0
   124.5    0.06       0  167.24    0.05       0
Bank Sta=108.7,124.5
XS Rating Curve= 0 ,0
Exp/Cntr(USF)=0,0
Exp/Cntr=0.3,0.1

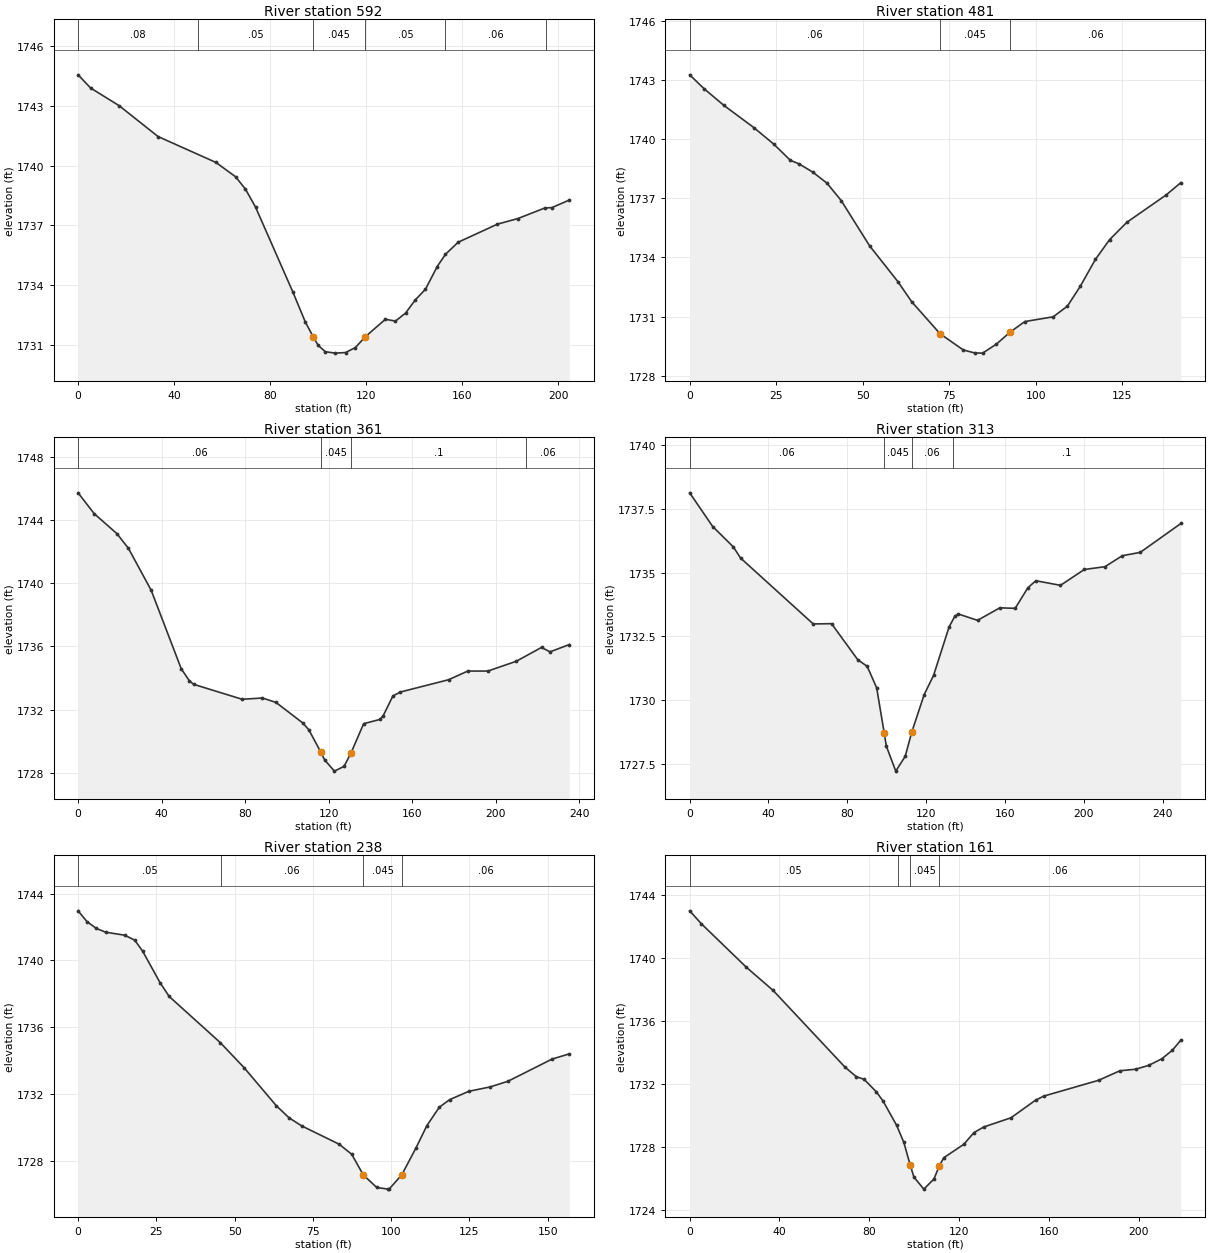
Type RM Length L Ch R = 1 ,592     ,109.7,110.8,111.6
XS GIS Cut Line= 4
2171141.29987692657283.3714382362171078.70846039657289.767641385
2170990.53223126657315.352453982 2170957.6374722657352.815929571
#Sta/Elev= 30
       0 1744.56     5.2  1743.9    17.1 1743.01    33.3 1741.46    57.4 1740.16
    65.6 1739.44    69.7 1738.82    73.9 1737.92    89.5 1733.64    94.7 1732.13
   97.95  1731.4     100 1730.97     103 1730.65   107.2 1730.58   111.4 1730.61
   115.5 1730.86   119.7 1731.41     128 1732.28   132.2 1732.19   136.4 1732.59
   140.5 1733.26   144.7 1733.79   149.6 1734.93     153 1735.54   158.3 1736.15
   174.7 1737.06   183.2 1737.34   194.4 1737.87   197.4 1737.89   204.6 1738.27
#Mann= 6, -1 ,  0
       0    0.08       0      50    0.05       0   97.95   0.045       0
   119.7    0.05       0  152.92    0.06       0  194.73     0.1       0
Bank Sta=97.95,119.7
XS Rating Curve= 0 ,0
Exp/Cntr(USF)=0,0
Exp/Cntr=0.3,0.1

Type RM Length L Ch R = 1 ,481     ,122.6,120.2,117.4
XS GIS Cut Line= 3
2171083.16945956657164.0004822322171062.61023515657184.559706641
2170952.04729499657207.403289317
#Sta/Elev= 28
       0 1743.25     4.2 1742.54     9.9  1741.7    18.6 1740.57    24.3 1739.74
    29.1 1738.92    31.6 1738.74    35.6 1738.32    39.7 1737.76    43.8 1736.88
      52 1734.59    60.2 1732.77    64.2 1731.75    72.4 1730.13    79.1 1729.31
    82.4 1729.16    84.7 1729.15    88.7 1729.61    92.6 1730.21    96.9 1730.75
   105.1 1730.99   109.2 1731.53   112.9 1732.53   117.3  1733.9   121.4  1734.9
   126.4 1735.78   137.8 1737.17     142 1737.79
#Mann= 3, -1 ,  0
       0    0.06       0    72.4   0.045       0    92.6    0.06       0
Bank Sta=72.4,92.6
XS Rating Curve= 0 ,0
Exp/Cntr(USF)=0,0
Exp/Cntr=0.3,0.1

Type RM Length L Ch R = 1 ,361     ,47.9,47.8,47.2
XS GIS Cut Line= 5
2171085.75448025656995.5181209942171025.80832911657060.307392617
2170975.67152214657090.2502078912170969.09280592657094.357122691
2170956.75668596657174.323508027
#Sta/Elev= 30
       0 1745.75     7.7 1744.43    18.6 1743.16    24.1 1742.23      35 1739.57
    49.4 1734.59    53.2 1733.84    55.3  1733.6    78.6 1732.65    88.3 1732.73
    94.8 1732.45   107.6 1731.15   110.5 1730.72   116.3 1729.29   118.1  1728.8
   122.8 1728.09   127.4 1728.39  130.66 1729.22   136.8  1731.1   144.6 1731.37
   146.1 1731.59   150.8 1732.86   154.4 1733.11   177.5 1733.89   186.7 1734.44
   196.3 1734.44   209.9 1735.06     222 1735.94   226.1 1735.66   235.3 1736.12
#Mann= 4, -1 ,  0
       0    0.06       0   116.3   0.045       0  130.66     0.1       0
  214.42    0.06       0
Bank Sta=116.3,130.66
XS Rating Curve= 0 ,0
Exp/Cntr(USF)=0,0
Exp/Cntr=0.3,0.1

Type RM Length L Ch R = 1 ,313     ,70.8,75.2,80.1
XS GIS Cut Line= 4
2171062.99619153656959.5093616022171013.97047191657014.348652894
2170932.49816058657068.6635271122170920.59073856657145.527639166
#Sta/Elev= 30
       0 1738.12    11.7  1736.8    22.2    1736    25.8 1735.57    62.7 1732.99
      72    1733    85.3 1731.59    90.1 1731.33    94.9 1730.49    98.7 1728.74
    99.8 1728.21   104.6 1727.23   109.4 1727.81  112.69 1728.75     119 1730.22
   123.8 1730.98   131.7 1732.88   134.6 1733.29   136.3 1733.38   146.1 1733.13
   157.4 1733.62   165.2  1733.6   171.7 1734.41   175.7 1734.68   188.2  1734.5
   200.3 1735.12   210.8 1735.23   219.6 1735.66   228.7 1735.79   249.3 1736.92
#Mann= 4, -1 ,  0
       0    0.06       0    98.7   0.045       0  112.69    0.06       0
  133.56     0.1       0
Bank Sta=98.7,112.69
XS Rating Curve= 0 ,0
Exp/Cntr(USF)=0,0
Exp/Cntr=0.3,0.1

Type RM Length L Ch R = 1 ,238     ,81.4,77.1,72.8
XS GIS Cut Line= 5
2171080.19010237656925.4485309622171065.97631759 656932.04778818
2171038.56401838656957.4295467092170971.04854069656956.414276368
 2170946.6820525656983.318940408
#Sta/Elev= 30
       0 1742.97     2.8 1742.33     5.8 1741.92     8.8 1741.69    14.9 1741.51
    18.1 1741.21    20.6 1740.56    26.2 1738.66    29.1 1737.84    45.4 1735.08
      53 1733.58    63.3  1731.3    67.4 1730.57    71.4 1730.09    83.4 1728.99
    87.4 1728.39    91.1 1727.15    95.4  1726.4      99  1726.3    99.4 1726.31
   103.4 1727.16     108 1728.79   111.4  1730.1   115.4 1731.21   118.7 1731.66
   124.8 1732.16   131.6 1732.42   137.3 1732.76   151.4 1734.09   156.9  1734.4
#Mann= 4, -1 ,  0
       0    0.05       0   45.67    0.06       0    91.1   0.045       0
   103.4    0.06       0
Bank Sta=91.1,103.4
XS Rating Curve= 0 ,0
Exp/Cntr(USF)=0,0
Exp/Cntr=0.3,0.1

Type RM Length L Ch R = 1 ,161     ,88.9,84.3,79.8
XS GIS Cut Line= 4
2171089.32753544656867.5781215162171016.73570604656867.578121516
2170947.69732285656901.0820427752170911.65522573656960.475357732
#Sta/Elev= 30
       0 1742.98     5.2 1742.16    25.2 1739.41    37.2 1737.93    69.2 1733.07
    74.2 1732.47    77.7  1732.3    83.2  1731.5    86.2 1730.91    92.2 1729.38
    95.4  1728.3    98.2 1726.88    99.9  1726.1   104.3 1725.34   108.8 1725.98
  111.25 1726.83   113.2 1727.33   122.1 1728.18   126.6 1728.92     131 1729.28
   143.1 1729.86   154.1 1730.98   157.8 1731.24   182.2 1732.24   191.6 1732.84
   198.6 1732.94   204.4 1733.18   210.3  1733.6   214.9 1734.13   218.8 1734.78
#Mann= 4, -1 ,  0
       0    0.05       0   92.59    0.06       0    98.2   0.045       0
  111.25    0.06       0
Bank Sta=98.2,111.25
XS Rating Curve= 0 ,0
Exp/Cntr(USF)=0,0
Exp/Cntr=0.3,0.1

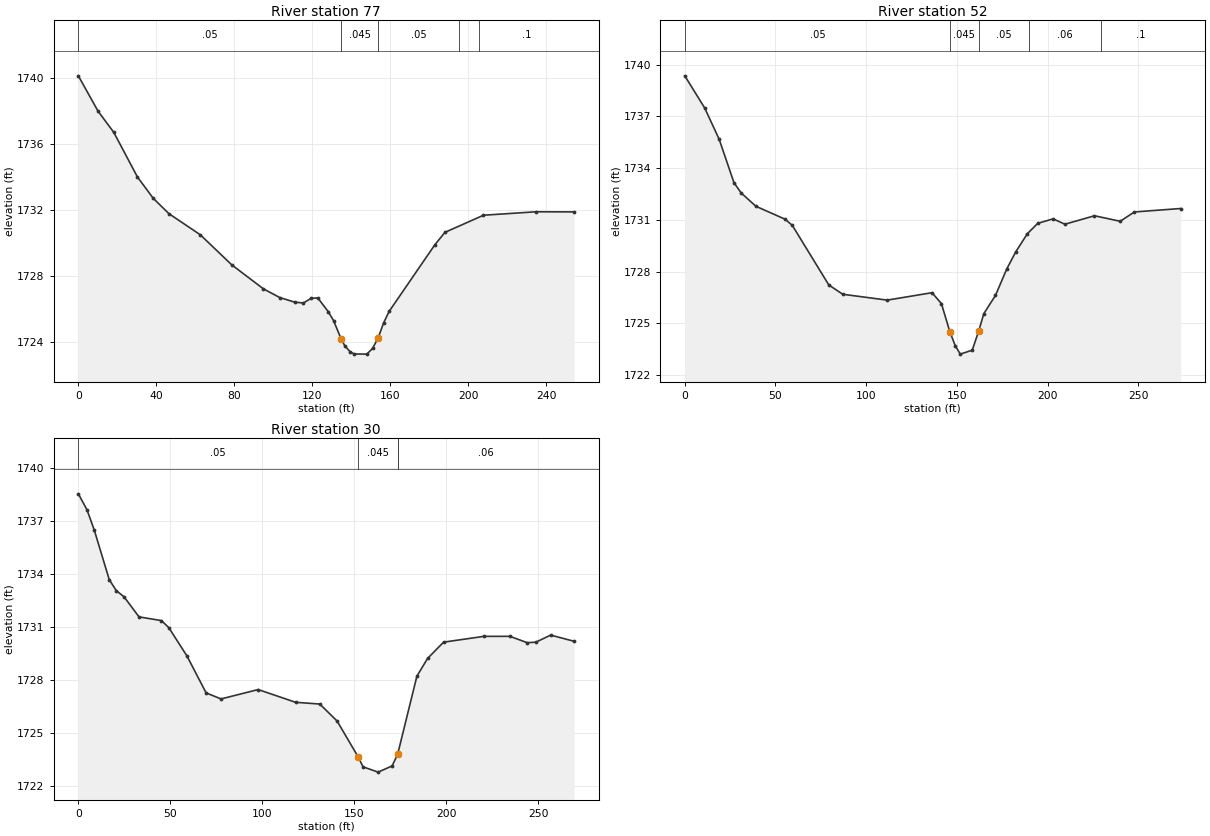
Type RM Length L Ch R = 1 ,77      ,24.2,24.6,25.3
XS GIS Cut Line= 3
2171070.17188454656806.9679136482170955.87603443 656791.21309825
2170872.50040369656902.372498432
#Sta/Elev= 30
       0 1740.16    10.1 1738.02    18.2 1736.73    30.3 1734.03    38.4 1732.74
    46.4 1731.81    62.6 1730.52    78.7  1728.7    94.9 1727.25   103.3 1726.72
     111 1726.44   115.4 1726.39   119.4 1726.67   122.8  1726.7   128.2 1725.86
   130.9 1725.32   134.9 1724.18   136.6 1723.81   139.4 1723.43   141.5  1723.3
     148 1723.29   150.9 1723.64   153.7 1724.25   156.6 1725.19   159.4 1725.88
   182.8 1729.91     188 1730.67   207.8 1731.71   234.9 1731.92   254.3 1731.91
#Mann= 5, -1 ,  0
       0    0.05       0   134.9   0.045       0   153.7    0.05       0
  195.38    0.06       0  205.38     0.1       0
Bank Sta=134.9,153.7
XS Rating Curve= 0 ,0
Exp/Cntr(USF)=0,0
Exp/Cntr=0.3,0.1

Type RM Length L Ch R = 1 ,52      ,21.2,22,21.2
XS GIS Cut Line= 3
2171067.06969789656790.8184249592170938.29039718656775.959617874
2170848.24051889656887.981041346
#Sta/Elev= 30
       0 1739.35      11 1737.48      19 1735.66    27.1 1733.16    31.1 1732.56
    39.2 1731.79    55.3 1731.04    59.3 1730.68    79.4 1727.23    87.1 1726.69
   111.6 1726.35   136.3 1726.78   141.5 1726.15   146.2  1724.5   149.1 1723.72
   151.9 1723.22   158.5 1723.45     162 1724.54   164.9 1725.57   171.3 1726.62
   177.5 1728.15   182.5 1729.15   188.9  1730.2   194.6  1730.8   203.1 1731.06
   209.6 1730.75   225.9 1731.24   240.1 1730.92   247.9 1731.46   273.4 1731.66
#Mann= 5, -1 ,  0
       0    0.05       0   146.2   0.045       0     162    0.05       0
  189.63    0.06       0  229.63     0.1       0
Bank Sta=146.2,162
XS Rating Curve= 0 ,0
Exp/Cntr(USF)=0,0
Exp/Cntr=0.3,0.1

Type RM Length L Ch R = 1 ,30      ,,,
XS GIS Cut Line= 3
2171060.77686695656780.1746175892170938.70110629656760.513850015
 2170814.4976267656837.189125398
#Sta/Elev= 30
       0 1738.54     4.7 1737.64     8.7 1736.48    16.8 1733.69    20.6 1733.07
    24.9 1732.71      33 1731.58    45.2 1731.37    49.2 1730.97      59 1729.38
    69.5 1727.28    77.6 1726.94    97.8 1727.47   118.1 1726.75   131.3 1726.65
   140.7 1725.69   152.1 1723.67   154.8  1723.1     163  1722.8   170.6 1723.15
   173.6  1723.8   184.1 1728.23   189.9 1729.23   198.6 1730.15   220.6 1730.48
   234.7 1730.48   244.1 1730.12   248.8 1730.15   256.8 1730.55   269.6  1730.2
#Mann= 4, -1 ,  0
       0    0.05       0   152.1   0.045       0   173.6    0.05       0
  173.65    0.06       0
Bank Sta=152.1,173.6
XS Rating Curve= 0 ,0
Exp/Cntr(USF)=0,0
Exp/Cntr=0.3,0.1
LCMann Table=0

Chan Stop Cuts=-1
Use User Specified Reach Order=0
Composite Channel Slope=5